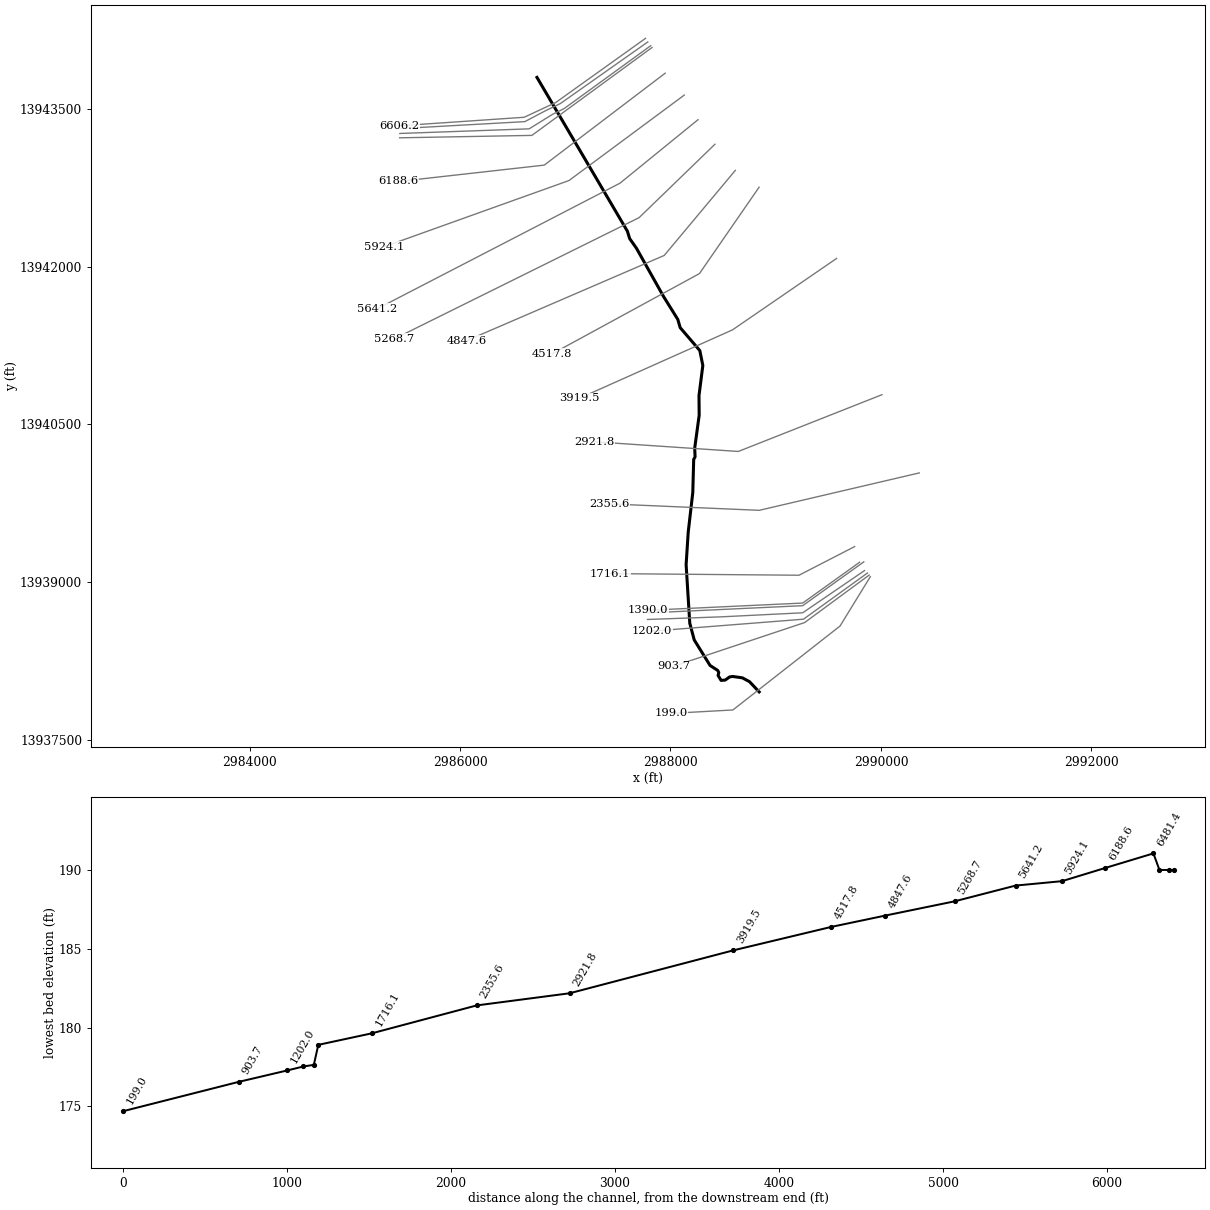
--- L114-00-00.PRJ (project) ---

Proj Title=L114-00-00
Current Plan=p03
Default Exp/Contr=.3,.1
English Units
Geom File=g01
Flow File=f02
Flow File=f03
Plan File=p02
Plan File=p03
Y Axis Title=Elevation
X Axis Title(PF)=Main Channel Distance
X Axis Title(XS)=Station
BEGIN DESCRIPTION:
Little Cypress Creek
Tributary 13.92 to Little Cypress
HCFCD Unit L114-00-00
Flood Hazard Model
10, 2, 1, 0.50-% Event
Filename L114-00-00.prj
Prepared by: Halff Associates, Inc. Date: 03/24/2004
Reviewed by: _____________   Date:  ___________
STATUS Final RAS
END DESCRIPTION:
DSS Export Rating Curves= 0
DSS Export Rating Curve Sorted= 0
DSS Export Volume Flow Curves= 0
DXF OffsetX= 0
DXF OffsetY= 0
DXF ScaleX= 1
DXF ScaleY= 10

--- L114-00-00.p03 (plan) ---

Plan Title=Floodway
Version=Version 3.0.1  Mar 2001
Short Identifier=Floodway0607
Geom File=g01
Flow File=f03
Subcritical Flow
K Sum by GR= 0
Std Step Tol= 0.01
Critical Tol= 0.01
Num of Std Step Trials= 20
Max Error Tol= 0.3
Flow Tol Ratio= 0.001
Split Flow NTrial= 30
Split Flow Tol= 0.02
Split Flow Ratio= 0.02
Log Output Level= 0
Friction Slope Method= 1
Unsteady Friction Slope Method= 2
Parabolic Critical Depth
Global Vel Dist= 0 , 0 , 0
Global Log Level= 0
CheckData=True
Encroach Param=-1 ,0,0, 2
Encroach River=L114-00-00
Encroach Reach=Reach - 1
Encroach Node=6606.2
       1    4978    5395
Encroach Node=6577.8
       1    4978    5450
Encroach Node=6547.9
       1    4978    5450
Encroach Node=6518.1
       1    4978    5450
Encroach Node=6481.4
       1  4932.8    5480
Encroach Node=6188.6
       1    4930    5400
Encroach Node=5924.1
       1    4900    5400
Encroach Node=5641.2
       1    4900    5400
Encroach Node=5268.7
       1  4970.7    5440
Encroach Node=4847.6
       1  4970.7    5440
Encroach Node=4517.8
       1    4970    5385
Encroach Node=3919.5
       1    4955    5320
Encroach Node=2921.8
       1    4860    5150
Encroach Node=2355.6
       1    4865    5080
Encroach Node=1716.1
       1    4855    5120
Encroach Node=1390.0
       1    4830    5150
Encroach Node=1362.7
       1    4830    5150
Encroach Node=1331.2
       1    4830    5150
Encroach Node=1299.7
       1    4830    5150
Encroach Node=1202.0
       1    4795    5140
Encroach Node=903.7
       1    4750    5120
Encroach Node=199.0
       1    4600    5280
Encroach Reach=L114-00-00_0002
Encroach Node=6606.2
       1    4978    5395
Encroach Node=6577.8
       1    4978    5450
Encroach Node=6547.9
       1    4978    5450
Encroach Node=6518.1
       1    4978    5450
Encroach Node=6481.4
       1  4932.8    5480
Encroach Node=6188.6
       1    4930    5400
Encroach Node=5924.1
       1    4900    5400
Encroach Node=5641.2
       1    4900    5400
Encroach Node=5268.7
       1  4970.7    5440
Encroach Node=4847.6
       1  4970.7    5440
Encroach Node=4517.8
       1    4970    5385
Encroach Node=3919.5
       1    4955    5320
Encroach Node=2921.8
       1    4860    5150
Encroach Node=2355.6
       1    4865    5080
Encroach Node=1716.1
       1    4855    5120
Encroach Node=1390.0
       1    4830    5150
Encroach Node=1362.7
       1    4830    5150
Encroach Node=1331.2
       1    4830    5150
Encroach Node=1299.7
       1    4830    5150
Encroach Node=1202.0
       1    4795    5140
Encroach Node=903.7
       1    4750    5120
Encroach Node=199.0
       1    4600    5280
Computation Interval=1HOUR
Output Interval=1HOUR
Run HTab= 0
Run UNet= 0
Run PostProcess= 0
UNET Theta= 1
UNET ZTol= 0.02
UNET ZSATol= 0.1
UNET MxIter= 20
UNET MaxInSteps= 20
UNET DtIC= 0
UNET DtMin= 0
UNET MaxCRTS= 20
UNET WFStab= 2
UNET SFStab= 1
UNET WFX= 1
UNET SFX= 1
UNET Convert EG Bridges=-1
UNET Use Existing IB Tables=-1
Instantaneous Interval=1HOUR
Write IC File= 0
Write Velocity= 0
Write Detailed= 0

--- L114-00-00.p02 (plan) ---

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Plan Title=FEMA Effective June 2007
Short Identifier=FEMAeff0607
Geom File=g01
Flow File=f02
Encroach Param=-1 ,0,0, 0

--- L114-00-00.f03 (steady flow) ---

Flow Title=Floodway
Version=Version 3.0.1  Mar 2001
Number of Profiles= 2
Profile Names=1PCT_100yr,1PCTFloodway_100yrFW
River Rch & RM=L114-00-00,L114-00-00_0002 ,6606.2
    1990    1990
River Rch & RM=L114-00-00,L114-00-00_0002 ,5641.2
    2090    2090
River Rch & RM=L114-00-00,L114-00-00_0002 ,4847.6
    2200    2200
River Rch & RM=L114-00-00,L114-00-00_0002 ,3919.5
    2280    2280
River Rch & RM=L114-00-00,L114-00-00_0002 ,903.7
    3678    3678
Boundary for River Rch & Prof#=L114-00-00,L114-00-00_0002 , 1
Up Type= 0
Dn Type= 3
Dn Slope=.0025
Boundary for River Rch & Prof#=L114-00-00,L114-00-00_0002 , 2
Up Type= 0
Dn Type= 1
Dn Known WS=186.77
DSS Import GetInterval= 0
DSS Import GetPeak= 0
DSS Import FillOption= 0

--- L114-00-00.f02 (steady flow) ---

Flow Title=FEMA Effective June 2007
Version=Version 3.0.1  Mar 2001
Number of Profiles= 4
Profile Names=10PCT_10yr,2PCT_50yr,1PCT_100yr,0.2PCT_500yr
River Rch & RM=L114-00-00,L114-00-00_0002 ,6606.2
    1060    1680    1990    3060
River Rch & RM=L114-00-00,L114-00-00_0002 ,5641.2
    1120    1760    2090    3210
River Rch & RM=L114-00-00,L114-00-00_0002 ,4847.6
    1200    1850    2200    3400
River Rch & RM=L114-00-00,L114-00-00_0002 ,3919.5
    1165    1900    2280    3414
River Rch & RM=L114-00-00,L114-00-00_0002 ,903.7
    1701    2966    3678    5912
Boundary for River Rch & Prof#=L114-00-00,L114-00-00_0002 , 1
Up Type= 0
Dn Type= 3
Dn Slope=.0025
Boundary for River Rch & Prof#=L114-00-00,L114-00-00_0002 , 2
Up Type= 0
Dn Type= 3
Dn Slope=.0025
Boundary for River Rch & Prof#=L114-00-00,L114-00-00_0002 , 3
Up Type= 0
Dn Type= 3
Dn Slope=.0025
Boundary for River Rch & Prof#=L114-00-00,L114-00-00_0002 , 4
Up Type= 0
Dn Type= 3
Dn Slope=.0025
DSS Import GetInterval= 0
DSS Import GetPeak= 0
DSS Import FillOption= 0

--- L114-00-00.g01 (geometry) ---

Geom Title=L114-00-00 June 2007
Version=Version 3.0.1  Mar 2001

River Reach=L114-00-00      ,L114-00-00_0002
Reach XY= 30
      2986731.07      13943797.7    2987590.2963    13942336.273
    2987611.9977   13942265.9605    2987677.1019   13942173.0786
    2987933.5856   13941716.2162     2988069.463   13941497.7313
    2988092.0324   13941419.6063    2988278.6644   13941201.7244
    2988307.3102   13941060.2313    2988270.8519    13940773.773
     2988272.588   13940587.1411    2988230.2366   13940275.9343
    2988233.5255   13940191.3077    2988220.5047   13940167.8702
    2988211.8241   13939852.7661    2988168.5106   13939476.8928
     2988148.456   13939167.8702    2988183.1984   13938610.5925
    2988225.7332   13938451.7384    2988375.9068   13938209.5509
    2988448.6386   13938162.1032    2988459.0553   13938142.1379
    2988452.1108   13938114.3601    2988480.7567   13938067.4851
    2988518.9511   13938070.0893    2988562.3539   13938100.4712
    2988590.9997   13938104.8115    2988682.9934   13938091.7767
    2988750.7009   13938055.3177    2988842.7165    13937958.095

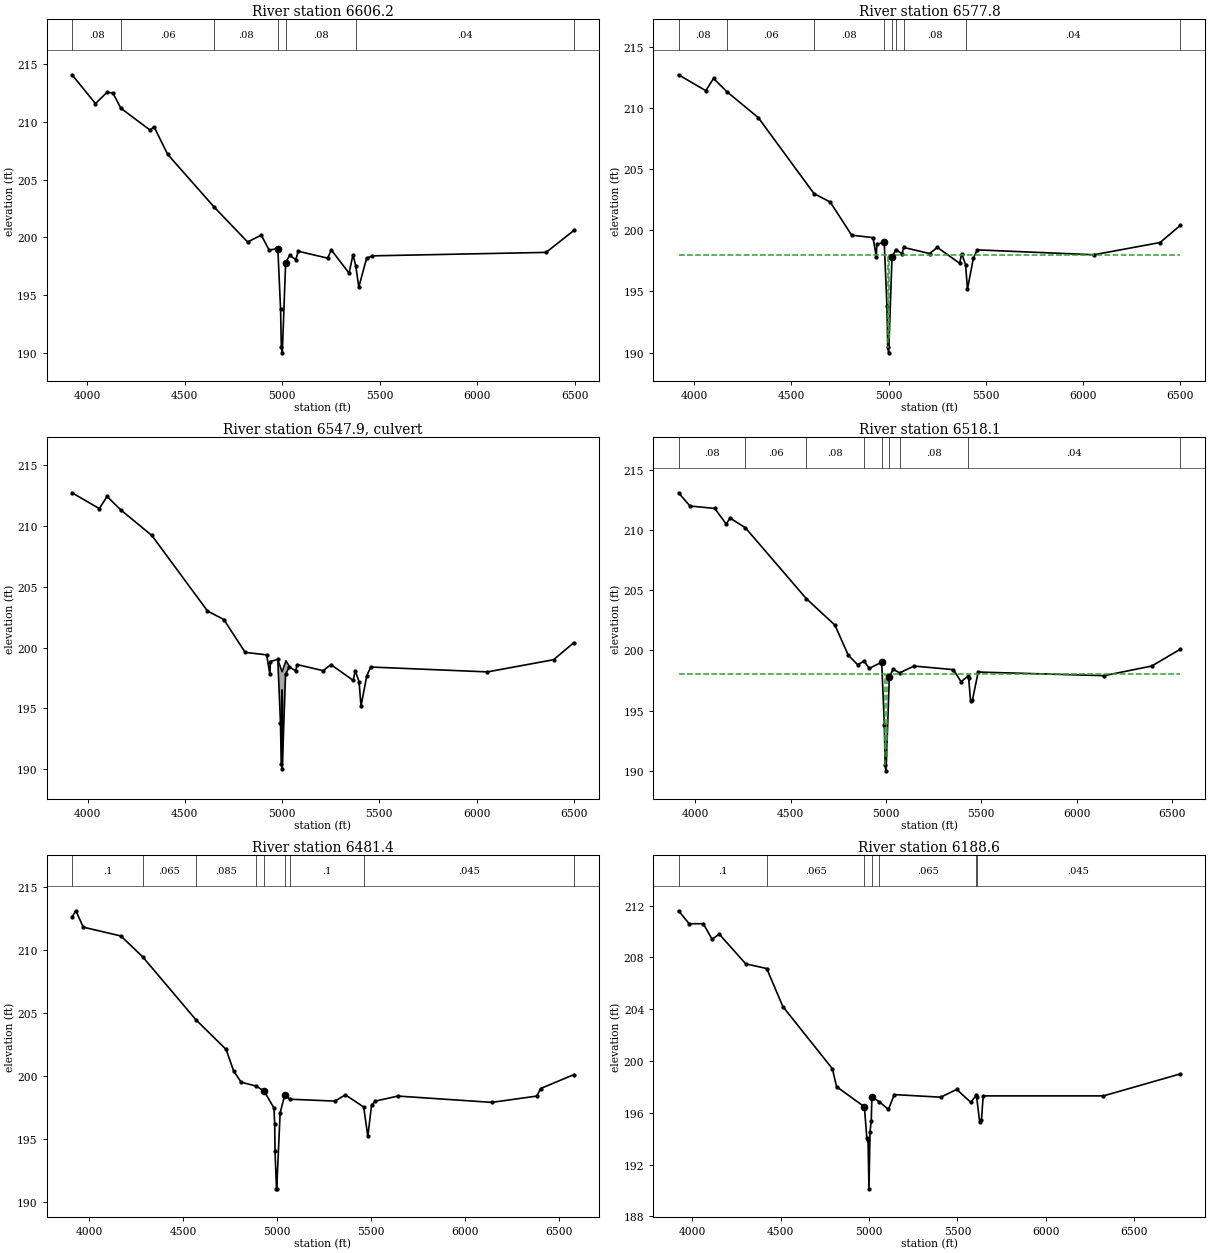
Type RM Length L Ch R = 1 ,6606.2  ,27.5,28.4,37.9
BEGIN DESCRIPTION:
Limits of Detailed Study (Approx old Xsec D in 1996 FIS)
Cross Section XS13
END DESCRIPTION:
XS GIS Cut Line= 4
       2987762.8     13944168.97      2986909.08     13943558.77
      2986609.58     13943418.81      2985419.98     13943337.64
#Sta/Elev= 30
  3923.2   214.1  4043.2   211.6  4103.2   212.6  4133.2   212.5  4173.2   211.2
  4323.2   209.3  4343.2   209.6  4413.2   207.2  4653.2   202.6  4823.2   199.6
  4893.2   200.2  4933.2   198.9    4978  199.03    4992  193.81    4996  190.46
    5001  189.99    5018   197.8    5038  198.44    5070  198.08  5082.6   198.8
  5232.6   198.2  5252.6   198.9  5343.2   196.9  5363.2   198.5  5377.1  197.55
  5393.2   195.7  5433.2   198.2  5463.2   198.4  6353.2   198.7  6495.5   200.6
#Mann= 7 ,-1 , 0
  3923.2     .08       0  4173.2     .06       0  4653.2     .08       0
    4978     .06       0    5018     .08       0  5377.1     .04       0
  6495.5      .2       0
Bank Sta=4978,5018
XS Rating Curve= 0
Exp/Cntr=.5,.3

Type RM Length L Ch R = 1 ,6577.8  ,57.9,59.7,65.5
BEGIN DESCRIPTION:
Upstream Face of Privite Rd. 5200' US of Bauer Hockley
END DESCRIPTION:
XS GIS Cut Line= 5
      2987784.24     13944134.55      2986952.93     13943548.78
       2986814.3     13943482.14      2986615.59      13943377.4
      2985433.22     13943311.56
#Sta/Elev= 30
  3920.6   212.7  4060.6   211.4  4100.6   212.4  4170.6   211.3  4330.6   209.2
  4616.8     203  4700.6   202.3  4810.6   199.6  4920.6   199.4  4937.6   197.8
    4940  198.85    4978  199.03    4992  193.81    4996  190.46    5001  189.99
    5018   197.8  5037.5  198.42    5070  198.08  5077.6   198.6  5211.4   198.1
  5251.4   198.6    5366   197.3    5376   198.1    5396   197.2    5406   195.2
    5436   197.7    5456   198.4    6056     198    6396     199  6500.2   200.4
#Mann= 9 ,-1 , 0
  3920.6     .08       0  4170.6     .06       0  4616.8     .08       0
    4978     .06       0    5018     .08       0  5037.5    .055       0
  5077.6     .08       0    5396     .04       0  6500.2      .2       0
#XS Ineff= 2 , 0
       0  4996.5  198.01  5003.5       0  198.01
Permanent Ineff=
       F       F
Bank Sta=4978,5018
XS Rating Curve= 0
Exp/Cntr=.5,.3

Type RM Length L Ch R = 2 ,6547.9  ,,,
BEGIN DESCRIPTION:
Private Rd. 5200' US of Bauer Hockley 1- 80" DIA CMP, 40' Long
END DESCRIPTION:
Bridge Culvert--1,0,-1,-1, 0
Deck Dist Width WeirC Skew NumUp NumDn MinLoCord MaxHiCord MaxSubmerge Is_Ogee
10,40,2.6,0, 5, 5, , , .95, 0, 0,0,,
    4978    5000    5020    5036  5037.5
  199.03  198.01  198.92   198.5  198.42
                                        
    4978    5000    5020    5036    5038
  199.03  198.01  198.92   198.5  198.44
                                        
BR Coef=-1 , 0 , 0 ,, 0 ,,,.8,-1,,0,
WSPro=,,,, 1 ,,,, 0 ,,,, 0 ,,,,-1 ,-1 ,-1 , 0 , 0 , 0 , 0 , 0
Culvert=1,6.67,,40,.027,.8,1,2,3,189.88,5000,189.87,5000,Culvert #1  , 0 ,10
Culvert Bottom n=.027
BC Design=,, 0 ,, 0 ,,,,,,

Type RM Length L Ch R = 1 ,6518.1  ,26.4,36.7,68.1
BEGIN DESCRIPTION:
Downstream Face of Privite Rd. 5200' US of Bauer Hockley
END DESCRIPTION:
XS GIS Cut Line= 5
      2987811.67     13944098.89      2986989.85     13943501.71
      2986874.84      13943444.2      2986656.74     13943308.81
      2985427.73     13943264.92
#Sta/Elev= 30
  3912.8   213.1  3972.8     212  4102.8   211.8  4162.8   210.5  4182.8     211
  4262.8   210.2  4583.4  204.29  4732.8   202.1  4802.8   199.6  4852.8   198.8
  4885.5  199.12  4912.8   198.5    4978  199.03    4992  193.81    4996  190.46
    5001  189.99    5018   197.8    5038  198.44  5071.6  198.13  5147.3   198.7
    5354   198.4    5394   197.4  5429.2  197.84    5434   197.7    5444   195.8
    5454   195.9    5484   198.2    6144   197.9    6394   198.7  6543.8   200.1
#Mann= 9 ,-1 , 0
  3912.8     .08       0  4262.8     .06       0  4583.4     .08       0
  4885.5    .055       0    4978     .06       0    5018    .055       0
  5071.6     .08       0  5429.2     .04       0  6543.8      .2       0
#XS Ineff= 2 , 0
       0  4996.5  198.01  5003.5       0  198.01
Permanent Ineff=
       F       F
Bank Sta=4978,5018
XS Rating Curve= 0
Exp/Cntr=.5,.3

Type RM Length L Ch R = 1 ,6481.4  ,289.59,292.8,335.12
BEGIN DESCRIPTION:
Cross Section XS10
END DESCRIPTION:
XS GIS Cut Line= 3
    2987824.4616   13944081.8422    2986682.7664   13943246.6424
    2985426.1354   13943223.6552
#Sta/Elev= 30
  3909.7   212.6  3929.7   213.1  3969.7   211.8  4169.7   211.1    4286  209.44
  4569.3  204.45  4729.7   202.1  4769.7   200.4  4809.7   199.5  4890.4  199.19
  4932.8  198.78  4984.5  197.45  4988.4  196.17  4990.2  194.01    4998  191.06
  4999.2  191.04  5017.4  197.07  5042.3  198.49  5069.9  198.15  5309.7     198
  5364.3   198.5  5462.2  197.53  5484.3   195.2  5504.3   197.7  5524.3     198
  5644.3   198.4  6144.3   197.9  6384.3   198.4  6404.3     199  6581.1   200.1
#Mann= 9 ,-1 , 0
  3909.7      .1       0    4286    .065       0  4569.3    .085       0
  4890.4    .065       0  4932.8    .065       0  5042.3    .065       0
  5069.9      .1       0  5462.2    .045       0  6581.1      .2       0
Bank Sta=4932.8,5042.3
XS Rating Curve= 0
Exp/Cntr=.3,.1

Type RM Length L Ch R = 1 ,6188.6  ,263.51,264.5,270.35
BEGIN DESCRIPTION:
Cross Section XS9.5
END DESCRIPTION:
XS GIS Cut Line= 4
    2987949.3188   13943837.5814    2986800.6105    13942964.219
    2985613.1817   13942830.8483 2985414.4314413 13942808.524889
#Sta/Elev= 30
    3923   211.6    3983   210.6    4063   210.6    4113   209.4    4153   209.8
    4303   207.5  4421.7  207.14    4513   204.2    4793   199.4  4816.9  198.01
  4974.1  196.46  4987.8  194.07  4994.7  193.88  5000.1  190.12  5005.9  194.53
    5013  195.37  5016.7  197.23  5059.2  196.84  5110.4  196.25    5143   197.4
    5406   197.2    5496   197.8    5576   196.8  5606.7  197.36  5608.8  197.23
    5626   195.3    5636   195.4    5646   197.3    6326   197.3  6760.9     199
#Mann= 7 ,-1 , 0
    3923      .1       0  4421.7    .065       0  4974.1    .065       0
  5016.7    .065       0  5059.2    .065       0  5606.7    .045       0
  5608.8    .045       0
Bank Sta=4974.1,5016.7
XS Rating Curve= 0
Exp/Cntr=.3,.1

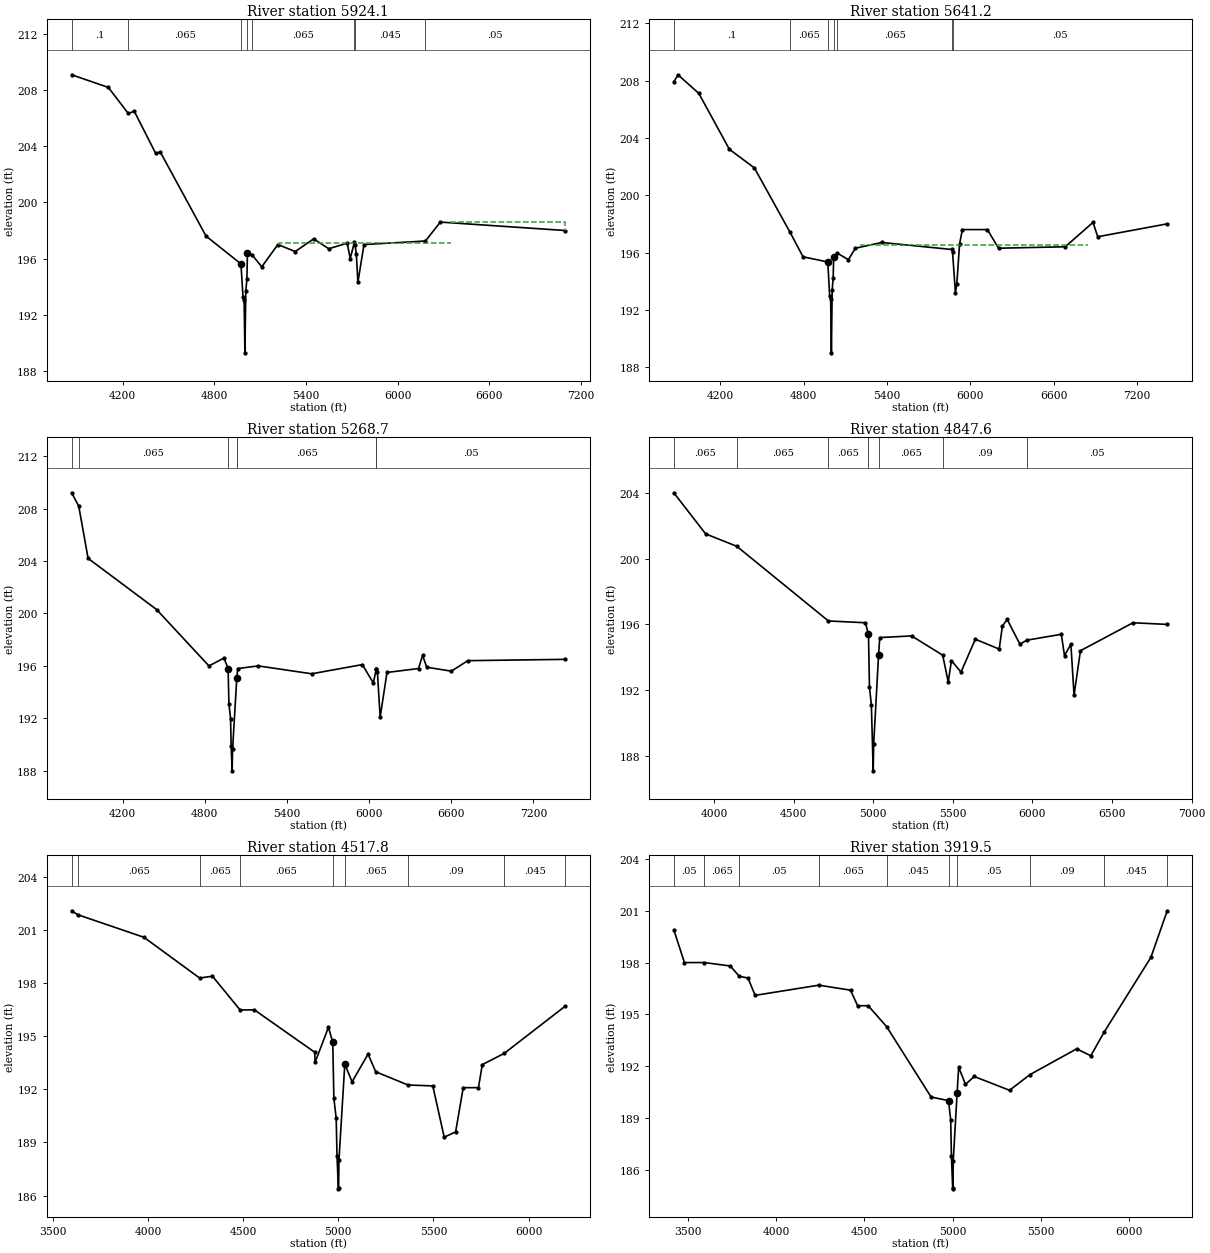
Type RM Length L Ch R = 1 ,5924.1  ,300.01,282.9,272.85
BEGIN DESCRIPTION:
Cross Section XS09
END DESCRIPTION:
XS GIS Cut Line= 4
     2988130.957   13943629.7616    2987035.2361   13942817.5489
    2985560.5653   13942289.5297 2985278.124781513942188.3993212
#Sta/Elev= 30
  3865.7   209.1  4105.7   208.2  4236.8  206.34  4275.7   206.5  4415.7   203.5
  4445.7   203.6  4745.7   197.6  4974.1  195.62  4987.8  193.23  4994.7  193.04
  5000.1  189.28  5005.9  193.69    5013  194.53  5016.7  196.39  5047.1  196.26
  5110.4  195.41  5215.7     197  5329.6   196.5  5449.6   197.4  5549.6   196.7
  5669.6   197.1  5689.6     196  5716.7  197.16  5721.2  196.97  5729.6   196.3
  5739.6   194.3  5779.6     197  6181.7  197.25  6279.6   198.6    7096     198
#Mann= 8 ,-1 , 0
  3865.7      .1       0  4236.8    .065       0  4974.1    .065       0
  5016.7    .065       0  5047.1    .065       0  5716.7    .045       0
  5721.2    .045       0  6181.7     .05       0
#XS Ineff= 2 ,-1
    5225    6350   197.1    6350    7150   198.6
Permanent Ineff=
       F       F
Bank Sta=4974.1,5016.7
XS Rating Curve= 0
Exp/Cntr=.3,.1

Type RM Length L Ch R = 1 ,5641.2  ,374.85,372.5,366.35
BEGIN DESCRIPTION:
Cross Section XS8.5
END DESCRIPTION:
XS GIS Cut Line= 4
    2988261.7195   13943395.8085    2987519.8589   13942792.3547
     2985660.063   13941830.1319  2985215.97945713941600.3715752
#Sta/Elev= 30
  3866.3   207.9  3896.3   208.4  4046.3   207.1  4266.3   203.2  4446.3   201.9
  4702.2  197.42  4796.3   195.7  4974.1  195.34  4987.8  192.95  4994.7  192.76
  5000.1     189  5005.9  193.41    5013  194.25  5016.7  195.72  5041.4  195.96
  5122.6   195.5  5172.6   196.3  5362.6   196.7  5867.4  196.21  5871.8  196.03
  5892.6   193.2  5902.6   193.8  5922.6   196.6  5942.6   197.6  6122.6   197.6
  6202.6   196.3  6682.6   196.4  6882.6   198.1  6916.6   197.1  7416.6     198
#Mann= 7 ,-1 , 0
  3866.3      .1       0  4702.2    .065       0  4974.1    .065       0
  5016.7    .065       0  5041.4    .065       0  5867.4     .05       0
  5871.8     .05       0
#XS Ineff= 2 ,-1
    5215    6850   196.5    6850    7500   197.8
Permanent Ineff=
       F       F
Bank Sta=4974.1,5016.7
XS Rating Curve= 0
Exp/Cntr=.3,.1

Type RM Length L Ch R = 1 ,5268.7  ,422.6,421.1,401.63
BEGIN DESCRIPTION:
Cross Section XS08
END DESCRIPTION:
XS GIS Cut Line= 4
      2988422.13     13943162.36      2987701.86     13942465.08
      2985730.37     13941488.77 2985371.9155707 13941311.258248
#Sta/Elev= 30
  3828.4   209.2  3880.3  208.18  3948.4   204.2  4448.4   200.3  4830.9     196
  4940.9   196.6  4970.7  195.79  4976.6  193.11  4988.8  191.99    4993  189.88
  5000.2     188  5003.3  189.63    5034  195.05  5034.2  195.07  5040.9   195.8
  5190.9     196  5580.9   195.4  5950.9   196.1  6030.9   194.7  6053.4   195.8
    6054  195.78  6060.9   195.5  6080.9   192.1  6130.9   195.5  6360.9   195.8
  6390.9   196.8  6420.9   195.9  6600.9   195.6  6720.9   196.4  7430.9   196.5
#Mann= 7 ,-1 , 0
  3828.4      .1       0  3880.3    .065       0  4970.7    .065       0
    5034    .065       0  5034.2    .065       0  6053.4     .05       0
    6054     .05       0
#XS Ineff= 1 ,-1
    5150    6750   195.8
Permanent Ineff=
       F
Bank Sta=4970.7,5034
XS Rating Curve= 0
Exp/Cntr=.3,.1

Type RM Length L Ch R = 1 ,4847.6  ,327.68,329.8,377.78
BEGIN DESCRIPTION:
Cross Section XS7.5
END DESCRIPTION:
XS GIS Cut Line= 4
    2988616.0409   13942914.1527    2987940.6156   13942105.8569
    2986246.5161   13941375.0689 2986062.873856713941295.8506795
#Sta/Elev= 30
  3748.2     204  3948.2   201.5  4143.3  200.75  4718.9  196.21  4951.5   196.1
  4970.7  195.39  4976.6  192.21  4988.8  191.09  5000.2   187.1  5003.3  188.73
    5034  194.15  5041.5   195.2  5241.5   195.3  5436.6  194.13  5471.5   192.5
  5491.5   193.8  5551.5   193.1  5641.5   195.1  5791.5   194.5  5811.5   195.9
  5841.5   196.3  5921.5   194.8  5964.4  195.04  6181.5   195.4  6201.5   194.1
  6241.5   194.8  6261.5   191.7  6301.5   194.4  6631.5   196.1  6846.5     196
#Mann= 7 ,-1 , 0
  3748.2    .065       0  4143.3    .065       0  4718.9    .065       0
  4970.7    .065       0    5034    .065       0  5436.6     .09       0
  5964.4     .05       0
#XS Ineff= 2 , 0
       0                    5225       0   194.4
Permanent Ineff=
       F       F
Bank Sta=4970.7,5034
XS Rating Curve= 0
Exp/Cntr=.3,.1

Type RM Length L Ch R = 1 ,4517.8  ,626.06,598.3,584.52
BEGIN DESCRIPTION:
Cross Section XS07
END DESCRIPTION:
XS GIS Cut Line= 3
    2988841.8252   13942753.9267    2988274.8925   13941933.1435
     2986874.326   13941170.1363
#Sta/Elev= 30
  3598.8   202.1  3630.5  201.88  3978.8   200.6  4270.9   198.3  4338.8   198.4
  4484.1  196.49  4558.8   196.5  4876.3   194.1  4877.9  193.53    4948  195.51
  4970.7  194.67  4976.6  191.49  4988.8  190.37    4993  188.26  5000.2  186.38
  5001.5  186.44  5003.3  188.01    5034  193.43  5072.4  192.43  5156.3     194
  5196.3     193  5365.9  192.25  5496.3   192.2  5556.3   189.3  5616.3   189.6
  5656.3   192.1  5736.3   192.1  5756.3   193.4  5871.9  194.04  6191.3   196.7
#Mann= 9 ,-1 , 0
  3598.8     .05       0  3630.5    .065       0  4270.9    .065       0
  4484.1    .065       0  4970.7    .065       0    5034    .065       0
  5365.9     .09       0  5871.9    .045       0  6191.3      .2       0
Bank Sta=4970.7,5034
XS Rating Curve= 0
Exp/Cntr=.3,.1

Type RM Length L Ch R = 1 ,3919.5  ,1046.06,997.7,884.43
BEGIN DESCRIPTION:
Cross Section XS06
END DESCRIPTION:
XS GIS Cut Line= 3
    2989577.9916   13942076.9921    2988588.7899   13941398.2329
    2987134.8471   13940748.7052
#Sta/Elev= 30
    3422   199.9    3482     198    3595     198    3742   197.8  3791.7  197.21
    3842   197.1    3882   196.1  4242.7  196.69    4422   196.4    4462   195.5
    4522   195.5  4626.1  194.29  4877.9  190.21  4976.6     190  4988.8  188.88
    4993  186.77  5000.2  184.89  5001.5  184.95  5003.3  186.52    5025  190.42
    5034  191.94  5072.4  190.94  5121.7   191.4  5321.7   190.6  5437.8  191.51
  5701.7     193  5781.7   192.6  5857.1  193.97  6121.7   198.3  6214.1     201
#Mann= 10 ,-1 , 0
    3422     .05       0    3595    .065       0  3791.7     .05       0
  4242.7    .065       0  4626.1    .045       0  4976.6    .065       0
    5025     .05       0  5437.8     .09       0  5857.1    .045       0
  6214.1      .2       0
Bank Sta=4976.6,5025
XS Rating Curve= 0
Exp/Cntr=.3,.1

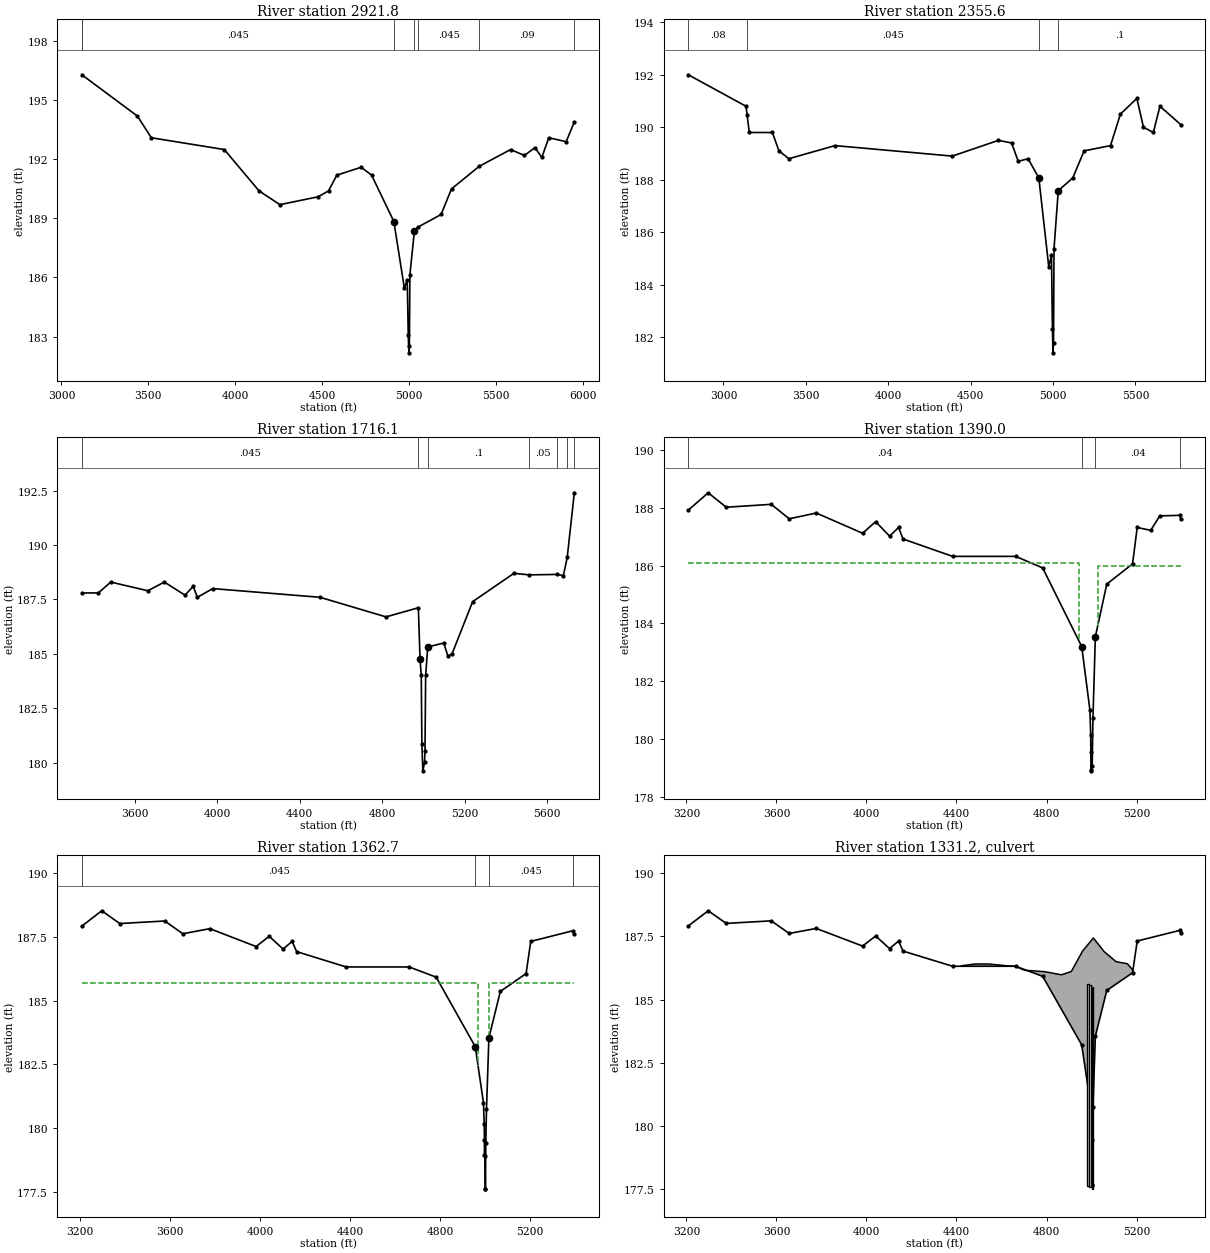
Type RM Length L Ch R = 1 ,2921.8  ,557.72,566.2,564.31
BEGIN DESCRIPTION:
Cross Section XS05
END DESCRIPTION:
XS GIS Cut Line= 3
    2990009.5374   13940782.3547    2988644.3367   13940242.9878
    2987280.4324   13940334.9365
#Sta/Elev= 30
  3117.6   196.3  3437.6   194.2  3517.6   193.1  3937.6   192.5  4137.6   190.4
  4257.6   189.7  4477.6   190.1  4537.6   190.4  4585.5   191.2  4725.5   191.6
  4785.5   191.2  4913.8  188.84  4974.2  185.45  4990.6  185.89  4996.5  183.09
  5000.1  182.17    5003  182.53    5006  186.14  5031.8  188.35  5052.5  188.56
  5185.5   189.2  5245.5   190.5  5405.3  191.65  5585.5   192.5  5665.5   192.2
  5725.5   192.6  5765.5   192.1  5805.5   193.1  5905.5   192.9  5952.5   193.9
#Mann= 7 , 1 , 0
  3117.6      .2       0  3117.6    .045       0  4913.8    .065       0
  5031.8     .09       0  5052.5    .045       0  5405.3     .09       0
  5952.5      .2       0
Bank Sta=4913.8,5031.8
XS Rating Curve= 0
Exp/Cntr=.3,.1

Type RM Length L Ch R = 1 ,2355.6  ,632.99,639.5,640.52
BEGIN DESCRIPTION:
Cross Section XS04
END DESCRIPTION:
XS GIS Cut Line= 4
 2990364.377547813940039.1498742    2990023.5658   13939959.4796
    2988843.5587   13939683.6338    2987418.3553   13939744.9329
#Sta/Elev= 30
    2787     192    3137   190.8  3143.9  190.46    3157   189.8    3297   189.8
    3337   189.1    3397   188.8    3677   189.3  4388.8   188.9  4668.8   189.5
  4748.8   189.4  4788.8   188.7  4848.8   188.8  4913.8  188.07  4974.2  184.68
  4990.6  185.12  4996.5  182.32  5000.1   181.4    5003  181.76    5006  185.37
  5031.8  187.58  5119.9  188.07  5188.8   189.1  5348.8   189.3  5408.8   190.5
  5508.8   191.1  5548.8     190  5608.8   189.8  5648.8   190.8  5775.3   190.1
#Mann= 4 ,-1 , 0
    2787     .08       0  3143.9    .045       0  4913.8    .065       0
  5031.8      .1       0
#XS Ineff= 2 ,-1
    2750    4685   189.3 5502.56 5649.95  190.73
Permanent Ineff=
       F       F
Bank Sta=4913.8,5031.8
XS Rating Curve= 0
Exp/Cntr=.3,.1

Type RM Length L Ch R = 1 ,1716.1  ,344.9,326.1,302.7
BEGIN DESCRIPTION:
Cross Section XS03
END DESCRIPTION:
XS GIS Cut Line= 3
    2989749.6356   13939338.8265    2989220.9311   13939066.8119
    2987427.9332   13939082.1367
#Sta/Elev= 30
  3343.9   187.8  3423.9   187.8  3483.9   188.3  3663.9   187.9  3743.9   188.3
  3843.9   187.7  3883.9   188.1  3903.9   187.6  3978.5     188  4498.5   187.6
  4818.5   186.7  4975.3  187.12  4983.6  184.75  4989.3  184.03  4992.5  180.86
    4997  179.63  5005.5  180.02  5007.5  180.55  5010.7  184.02  5020.8  185.32
  5098.5   185.5  5118.5   184.9  5138.5     185  5238.5   187.4  5438.5   188.7
    5513  188.63  5646.3  188.65  5678.5   188.6    5697  189.43  5731.5   192.4
#Mann= 7 ,-1 , 0
  3343.9    .045       0  4975.3    .065       0  5020.8      .1       0
    5513     .05       0  5646.3     .07       0    5697      .1       0
  5731.5      .2       0
#XS Ineff= 2 , 0
       0    3500                       0
Permanent Ineff=
       T       F
Bank Sta=4983.6,5020.8
XS Rating Curve= 0
Exp/Cntr=.3,.1

Type RM Length L Ch R = 1 ,1390.0  ,40.5,27.3,26.4
BEGIN DESCRIPTION:
Cross Section s01-us
END DESCRIPTION:
XS GIS Cut Line= 3
     2989797.122   13939190.2358    2989256.2728   13938802.3463
    2987784.2341   13938733.4982
#Sta/Elev= 30
  3208.8  187.92  3297.2  188.52  3377.2  188.02  3577.2  188.12  3657.2  187.62
  3777.2  187.82  3982.8  187.12    4041  187.52  4102.8  187.02  4142.8  187.32
  4162.8  186.92  4382.8  186.32  4662.8  186.32  4782.8  185.92  4956.3   183.2
  4992.6  181.01  4996.2  180.15    4997  179.55  4997.1  178.94  4999.6   178.9
  5002.8  179.07  5006.2  180.74  5016.9  183.54  5067.6  185.36  5182.1  186.06
  5202.8  187.32  5262.8  187.22  5302.8  187.72  5390.9  187.74  5396.4  187.62
#Mann= 4 ,-1 , 0
  3208.8     .04       0  4956.3     .06       0  5016.9     .04       0
  5390.9      .2       0
#XS Ineff= 2 , 0
       0  4946.3   186.1  5026.9       0  185.98
Permanent Ineff=
       F       F
Bank Sta=4956.3,5016.9
XS Rating Curve= 0
Exp/Cntr=.5,.3

Type RM Length L Ch R = 1 ,1362.7  ,70.4,63,56.4
BEGIN DESCRIPTION:
Upstream Section of Bauer Hockley Road
END DESCRIPTION:
XS GIS Cut Line= 3
     2989836.859   13939193.7509    2989256.2728   13938777.3626
    2987784.7336   13938708.5378
#Sta/Elev= 30
  3208.8  187.92  3297.2  188.52  3377.2  188.02  3577.2  188.12  3657.2  187.62
  3777.2  187.82  3982.8  187.12    4041  187.52  4102.8  187.02  4142.8  187.32
  4162.8  186.92  4382.8  186.32  4662.8  186.32  4782.8  185.92  4956.3   183.2
  4992.6  181.01  4996.2  180.15    4997  179.55  4997.1  178.94  4999.6   178.9
 5001.08  177.63 5001.65  177.63  5003.1  179.42  5006.2  180.74  5016.9  183.54
  5067.6  185.36  5182.1  186.06  5202.8  187.32  5390.9  187.74  5396.4  187.62
#Mann= 4 ,-1 , 0
  3208.8    .045       0  4956.3    .065       0  5016.9    .045       0
  5390.9      .2       0
#XS Ineff= 2 , 0
       0  4969.1   185.7  5018.2       0   185.7
Permanent Ineff=
       F       F
Bank Sta=4956.3,5016.9
XS Rating Curve= 0
Exp/Cntr=.5,.3

Type RM Length L Ch R = 2 ,1331.2  ,,,
BEGIN DESCRIPTION:
BAUER-HOCKLEY- 3- 8'x8' CBC
Structure ID: L114-00-00-S1
END DESCRIPTION:
Bridge Culvert--1,0,-1,-1, 0
Deck Dist Width WeirC Skew NumUp NumDn MinLoCord MaxHiCord MaxSubmerge Is_Ogee
10,43,3,0, 18, 18, , , .95, 0, 1,1,,
  4422.8  4482.8  4542.8    4621    4641  4662.8  4702.8  4782.8  4795.3    4866
    4910    4960    5008    5057    5109    5159  5182.1    5185
  186.34  186.41  186.41  186.34  186.33  186.31  186.16  186.11   186.1  185.98
  186.11  186.92  187.44  186.89   186.5  186.42  186.18186.1565
                                                                                
                                                                
  4422.8  4482.8  4542.8    4621    4641  4662.8  4702.8  4782.8  4795.3    4866
    4910    4960    5008    5057    5109    5159  5182.1    5185
  186.34  186.41  186.41  186.34  186.33  186.31  186.16  186.11   186.1  185.98
  186.11  186.92  187.44  186.89   186.5  186.42  186.18186.1565
                                                                                
                                                                
BR Coef= 1 , 0 , 0 ,1.25, 0 ,,,.8,-1,2,0,
WSPro=,,,, 1 ,,,, 0 ,,,, 0 ,,,,-1 ,-1 ,-1 , 0 , 0 , 0 , 0 , 0
Culvert=2,8,8,43,.015,.4,1,10,1,177.62,4983.1,177.53,4983.1,Culvert #1  , 0 ,10
Culvert Bottom n=.015
Culvert=2,8,8,43,.015,.4,1,10,1,177.58,4993.8,177.56,4993.8,Culvert #2  , 0 ,10
Culvert Bottom n=.015
Culvert=2,8,8,43,.015,.4,1,10,1,177.49,5004.2,177.53,5004.2,Culvert #3  , 0 ,10
Culvert Bottom n=.015
BC Design=,, 0 ,, 0 ,,,,,,
BC HTab HWMax=188.52

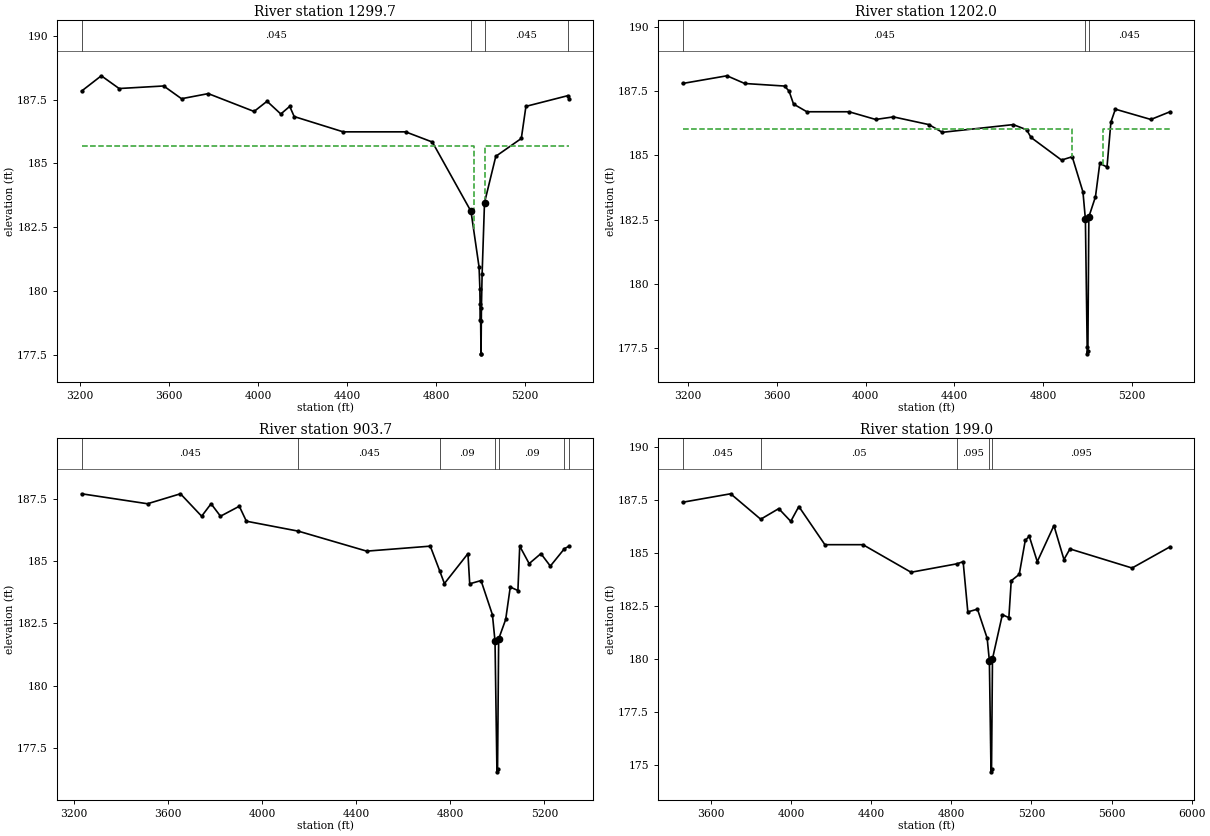
Type RM Length L Ch R = 1 ,1299.7  ,92.8,97.7,102
BEGIN DESCRIPTION:
Downstream Section of Bauer Hockley Road- 3-8x8 Box Culverts
END DESCRIPTION:
XS GIS Cut Line= 4
    2989843.6577    13939110.752    2989256.2091   13938709.8407
    2988482.8951   13938671.4152    2987781.1501   13938646.3529
#Sta/Elev= 30
  3208.8  187.84  3297.2  188.44  3377.2  187.94  3577.2  188.04  3657.2  187.54
  3777.2  187.74  3982.8  187.04    4041  187.44  4102.8  186.94  4142.8  187.24
  4162.8  186.84  4382.8  186.24  4662.8  186.24  4782.8  185.84  4956.3  183.12
  4992.6  180.93  4996.2  180.07    4997  179.47  4997.1  178.86  4999.6  178.82
 5001.16  177.53 5001.48  177.53  5003.1  179.34  5006.2  180.66  5016.9  183.46
  5067.6  185.28  5182.1  185.98  5202.8  187.24  5390.9  187.66  5396.4  187.54
#Mann= 4 ,-1 , 0
  3208.8    .045       0  4956.3    .065       0  5016.9    .045       0
  5390.9      .2       0
#XS Ineff= 2 , 0
       0  4969.1   185.7  5018.2       0   185.7
Permanent Ineff=
       F       F
Bank Sta=4956.3,5016.9
XS Rating Curve= 0
Exp/Cntr=.5,.3

Type RM Length L Ch R = 1 ,1202.0  ,199.2,298.3,322.6
BEGIN DESCRIPTION:
Cross section extends to limits of DA divide. Cannot extend xsec to limits of the BFE
Cross Section XS02
END DESCRIPTION:
XS GIS Cut Line= 3
    2989871.9036   13939088.0342    2989263.7042   13938649.0074
    2987821.8827   13938535.3929
#Sta/Elev= 30
  3175.3   187.8  3375.3   188.1  3455.3   187.8  3635.3   187.7  3655.3   187.5
  3675.3     187  3735.3   186.7  3925.4   186.7  4045.4   186.4  4125.4   186.5
  4285.4   186.2  4345.4   185.9  4665.4   186.2  4725.4     186  4745.4   185.7
  4882.9  184.82    4931  184.95  4979.4  183.58  4990.4  182.52  4998.4  177.54
  4998.6  177.28  5001.6   177.4  5005.9  182.61  5035.7  183.39  5055.2  184.69
  5087.7  184.55  5105.4   186.3  5125.4   186.8  5285.4   186.4  5371.7   186.7
#Mann= 3 ,-1 , 0
  3175.3    .045       0  4990.4    .065       0  5005.9    .045       0
#XS Ineff= 2 , 0
       0    4930  186.03    5070       0  186.03
Permanent Ineff=
       F       F
Bank Sta=4990.4,5005.9
XS Rating Curve= 0
Exp/Cntr=.3,.1

Type RM Length L Ch R = 1 ,903.7   ,403.7,704.7,558.7
BEGIN DESCRIPTION:
Cross section extends to limits of DA divide. Cannot extend xsec to limits of the BFE
Surveyed FL= 176.52
Cross Section XS1.5
END DESCRIPTION:
XS GIS Cut Line= 3
      2989887.95     13939068.22      2989274.79     13938617.03
      2988032.34     13938202.88
#Sta/Elev= 30
  3234.1   187.7  3514.1   187.3  3654.1   187.7  3744.1   186.8  3784.1   187.3
  3824.1   186.8  3904.1   187.2  3934.1   186.6  4155.4   186.2  4445.4   185.4
  4715.4   185.6    4755  184.62  4775.4   184.1  4875.4   185.3  4882.9  184.09
    4931  184.22  4979.4  182.85  4990.4  181.79  4998.6  176.55  5001.2  176.67
  5005.9  181.88  5035.7  182.66  5055.2  183.96  5087.7  183.82  5095.4   185.6
  5135.4   184.9  5185.4   185.3  5225.4   184.8  5285.4   185.5    5305   185.6
#Mann= 7 ,-1 , 0
  3234.1    .045       0  4155.4    .045       0    4755     .09       0
  4990.4     .06       0  5005.9     .09       0  5285.4    .045       0
    5305      .2       0
Bank Sta=4990.4,5005.9
XS Rating Curve= 0
Exp/Cntr=.3,.1

Type RM Length L Ch R = 1 ,199.0   ,0,0,0
BEGIN DESCRIPTION:
Cross section extends to limits of DA divide. Cannot extend xsec to limits of the BFE
Cross Section XS01
END DESCRIPTION:
XS GIS Cut Line= 4
      2989898.93     13939052.86      2989611.03     13938583.83
      2988593.06     13937786.42      2988004.62       13937754.
#Sta/Elev= 30
  3459.2   187.4  3699.2   187.8  3849.2   186.6  3939.2   187.1  3999.2   186.5
  4039.5   187.2  4169.5   185.4  4359.5   185.4  4599.5   184.1  4829.5   184.5
  4859.5   184.6  4882.9  182.23    4931  182.36  4979.4  180.99  4990.4  179.93
  4998.6  174.69  5001.2  174.81  5005.9  180.02  5055.2   182.1  5087.7  181.96
  5099.5   183.7  5139.5     184  5169.5   185.6  5189.5   185.8  5229.5   184.6
  5312.6   186.3  5362.6   184.7  5392.6   185.2  5702.6   184.3    5892   185.3
#Mann= 5 ,-1 , 0
  3459.2    .045       0  3849.2     .05       0  4829.5    .095       0
  4990.4    .065       0  5005.9    .095       0
Bank Sta=4990.4,5005.9
XS Rating Curve= 0
Exp/Cntr=.3,.1

Chan Stop Cuts=-1